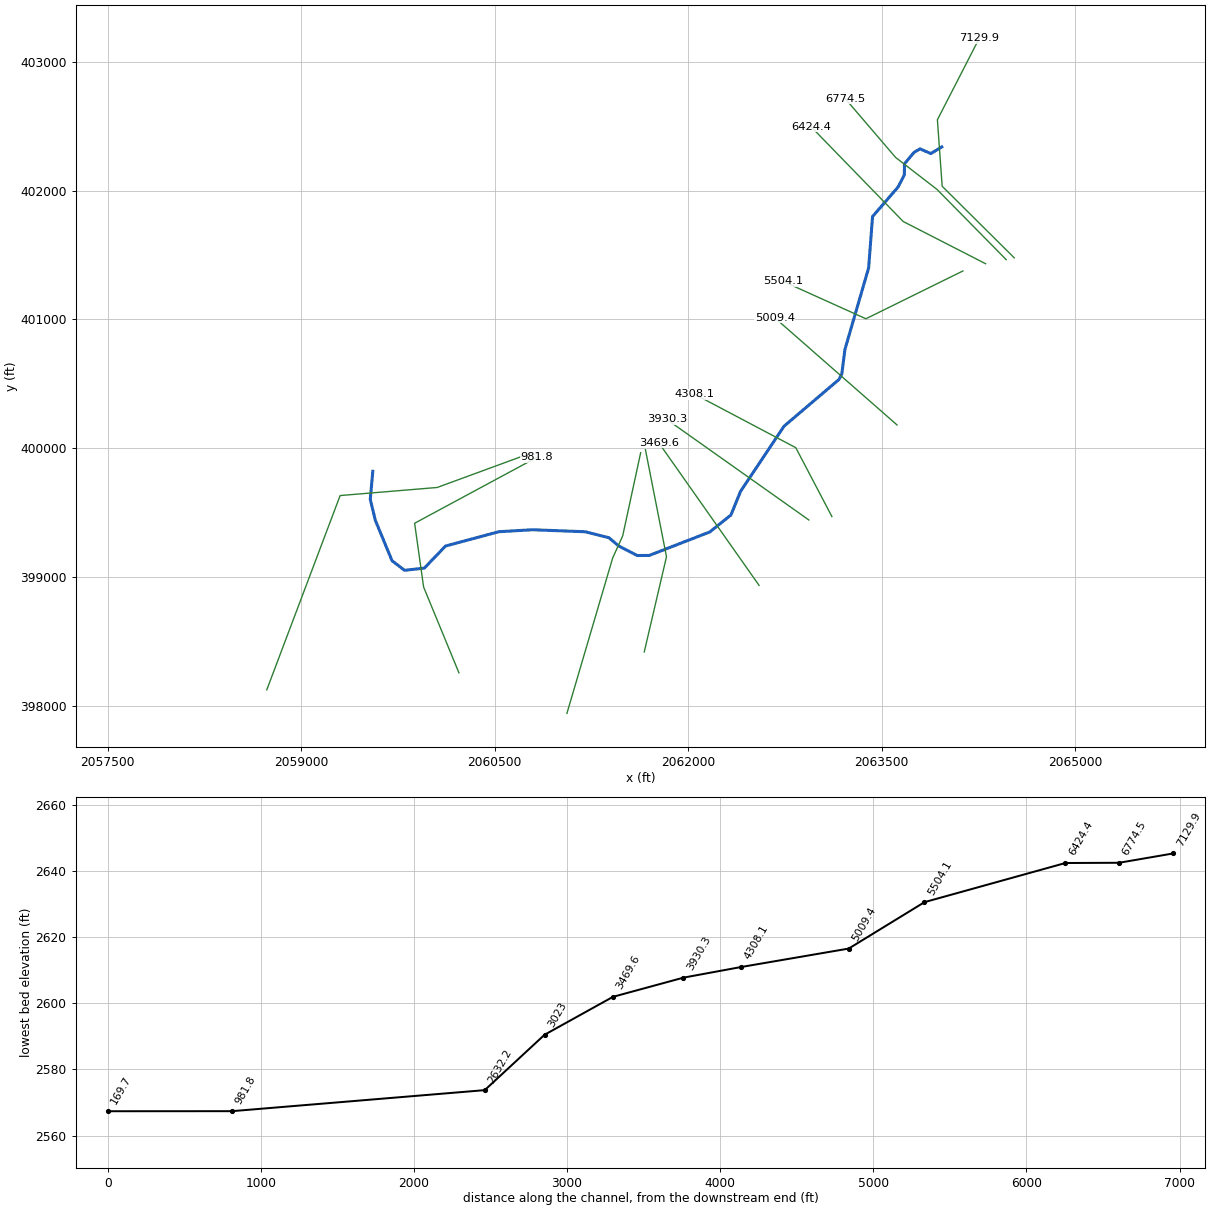
--- HominyCr.prj (project) ---

Proj Title=HominyCr
Current Plan=p01
Default Exp/Contr=0,0
English Units
Geom File=g01
Flow File=f01
Plan File=p01
BEGIN DESCRIPTION:
END DESCRIPTION:
DSS Export Rating Curves= 0
DSS Export Rating Curve Sorted= 0
DSS Export Volume Flow Curves= 0
DXF OffsetX= 0
DXF OffsetY= 0
DXF ScaleX= 0
DXF ScaleY= 0

--- HominyCr.p01 (plan) ---

Plan Title=Floodplain
Program Version=4.00
Geom File=g01
Flow File=f01
K Sum by GR=0
Std Step Tol=0.01
Critical Tol=0.01
Num of Std Step Trials=20
Max Error Tol=0.3
Flow Tol Ratio=0.001
Split Flow NTrial=30
Split Flow Tol=0.02
Split Flow Ratio=0.02
Log Output Level=0
Friction Slope Method=1
Unsteady Friction Slope Method=2
Unsteady Bridges Friction Slope Method=1
Global Log Level=0
CheckData=False
Run HTab=0
Run UNet=0
Run PostProcess=0
UNET Theta=0
UNET Theta Warmup=0
UNET ZTol=0
UNET ZSATol=0
UNET MxIter=0
UNET MaxInSteps=0
UNET DtIC=0
UNET DtMin=0
UNET MaxCRTS=0
UNET WFStab=0
UNET SFStab=0
UNET WFX=0
UNET SFX=0
UNET DSS MLevel=0
UNET DZMax Abort=0
UNET Convert EG Bridges=0
UNET Use Existing IB Tables=0
UNET Froude Limit=0
UNET Froude Power=0
Write IC File=0
Echo Input=False
Echo Output=False
Write Detailed=0

--- HominyCr.f01 (steady flow) ---

Flow Title=Moglen and others (2006)
Program Version=4.00
Number of Profiles=1
Profile Names=P100yr
River Rch & RM=HominyCr,Main      ,7129.9
483.7386
River Rch & RM=HominyCr,Main      ,6774.5
517.1070
River Rch & RM=HominyCr,Main      ,6424.4
818.3501
River Rch & RM=HominyCr,Main      ,4308.1
844.0682
River Rch & RM=HominyCr,Main      ,3930.3
962.8261
River Rch & RM=HominyCr,Main      ,3469.6
964.5964
River Rch & RM=HominyCr,Main      ,3023
1151.425
River Rch & RM=HominyCr,Main      ,981.8
1173.385
River Rch & RM=HominyCr,Main      ,169.7
1561.302
Boundary for River Rch & Prof#=HominyCr,Main      ,1
Up Type=0
Dn Type=3
Dn Slope=0.002

--- HominyCr.g01 (geometry) ---

Geom Title=USGS 10m DEM
Program Version=4.10

River Reach=HominyCr        ,Main
Reach XY= 30
     2063966.014      402339.494     2063881.097      402287.728
     2063797.423      402324.453     2063751.045      402296.877
     2063677.091      402208.507      2063675.76      402122.065
     2063627.112      402027.378     2063429.536      401798.665
       2063399.1      401399.215     2063215.354      400766.039
     2063191.497      400575.715     2063167.732      400531.581
     2062743.576      400170.108     2062405.882      399663.567
     2062332.068      399480.499      2062167.51      399348.221
     2061698.565       399165.96     2061605.204      399165.111
     2061460.918        399239.8     2061385.351      399303.526
     2061202.094      399349.796     2060793.809      399365.413
     2060532.397      399350.136     2060118.999      399238.967
     2059955.118      399067.637     2059801.169      399050.255
      2059704.33      399124.747     2059575.212       399437.61
     2059535.483      399601.491     2059555.348      399819.999

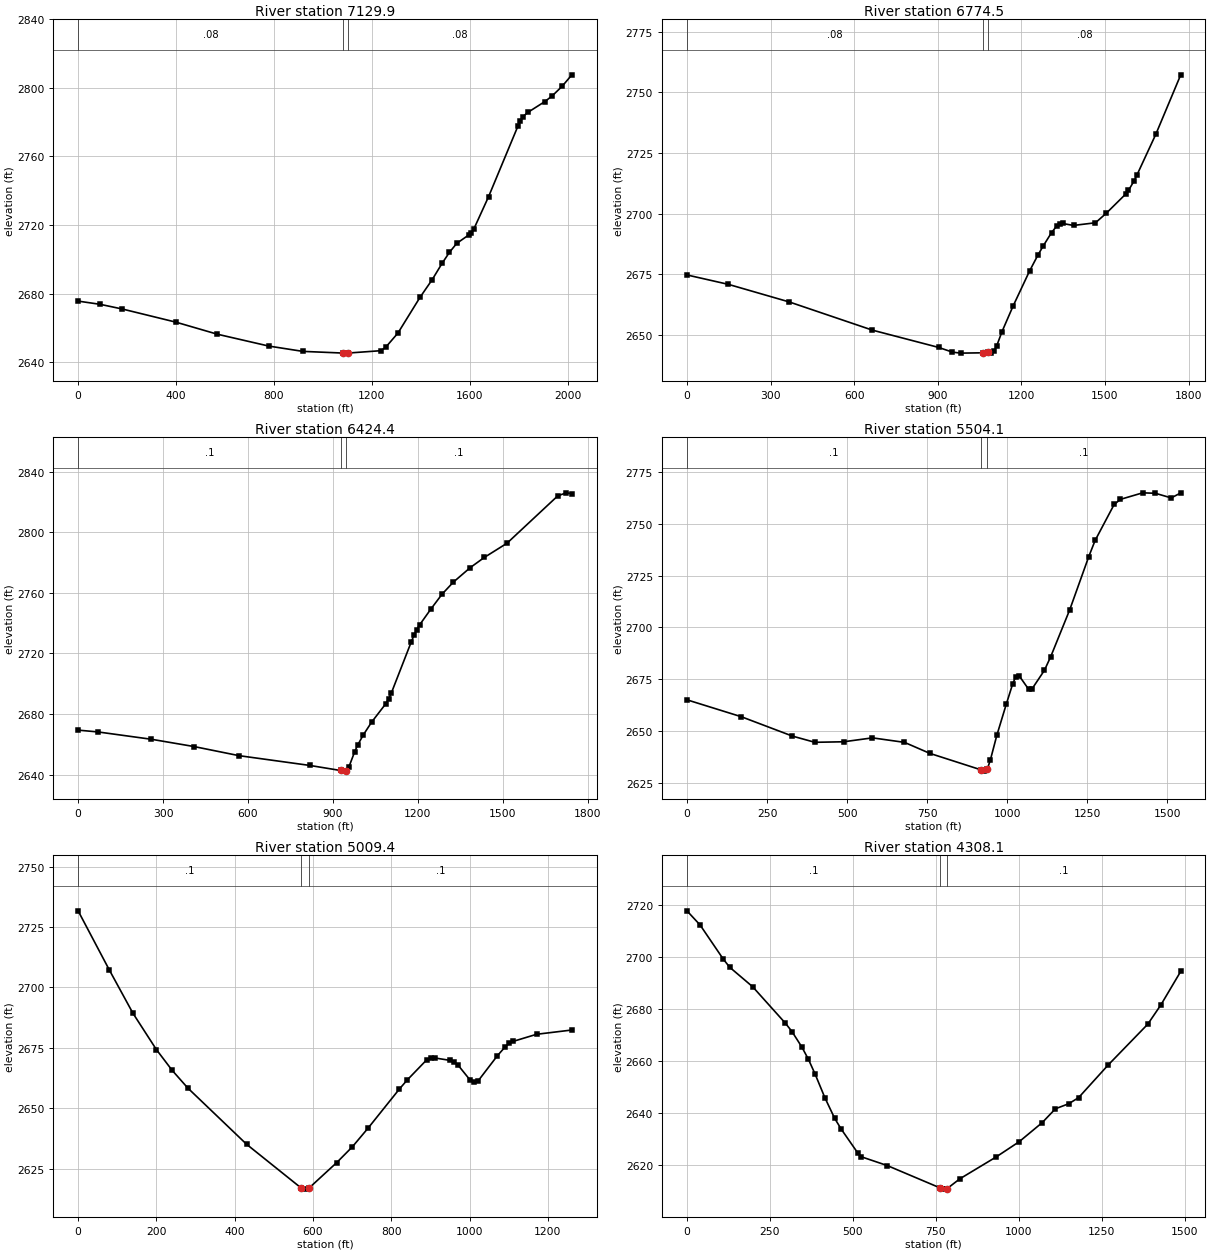
Type RM Length L Ch R = 1 ,7129.9  ,329.6,355.4,380.1
XS GIS Cut Line= 4
     2064528.389      401477.479     2063969.332      402033.825
     2063932.297      402550.555     2064256.666      403183.061
#Sta/Elev= 30
       0 2675.58    89.8 2673.71   179.7    2671   399.4 2663.31   569.1 2656.26
   778.7 2649.36   918.2 2646.25  1083.22645.262 1097.66 2645.23 1103.492645.276
    1237 2646.65    1257 2648.68  1306.8 2656.93  1396.9 2677.75  1446.9 2688.11
    1487 2697.56    1517 2703.98    1547 2709.25  1597.1 2714.26  1607.1 2715.57
  1617.1 2717.69  1677.2 2736.51  1797.3 2777.73  1807.4 2780.85  1817.4  2783.2
  1837.4 2785.66  1907.5 2792.03  1937.5 2795.36  1977.6 2800.89  2017.6  2807.6
#Mann= 3 , 0 , 0
       0     .08       0  1083.2    .045       0 1103.49     .08       0
Bank Sta=1083.2,1103.49
XS Rating Curve= 0 ,0
Exp/Cntr=0.3,0.1

Type RM Length L Ch R = 1 ,6774.5  ,352.9,350.1,346.4
XS GIS Cut Line= 4
     2064465.683      401463.632     2063929.554      402009.167
     2063608.857      402257.167      2063217.85      402714.601
#Sta/Elev= 30
       0 2674.65     149 2670.76   367.5  2663.5   665.6 2651.88   903.3 2644.75
   952.8 2642.81   982.4  2642.4  1061.5 2642.53  1081.3 2642.66  1091.2 2642.64
  1101.1 2643.15    1111 2645.19  1130.7 2651.28  1170.3 2661.78  1229.5 2676.26
  1259.1 2682.75  1278.8 2686.65  1308.4  2692.1  1328.1    2695    1338 2695.74
  1347.9 2695.89  1387.3 2695.08  1466.2 2696.18  1505.7  2700.2  1574.8 2708.04
  1584.6 2709.53  1604.4 2713.39  1614.2 2715.68  1683.3 2732.84  1772.1 2757.21
#Mann= 3 , 0 , 0
       0     .08       0  1061.5    .045       0  1081.3     .08       0
Bank Sta=1061.5,1081.3
XS Rating Curve= 0 ,0
Exp/Cntr=0.3,0.1

Type RM Length L Ch R = 1 ,6424.4  ,908.7,920.2,931.6
XS GIS Cut Line= 3
     2064305.785      401432.279     2063666.976      401760.241
     2062952.136      402497.027
#Sta/Elev= 30
       0 2669.39    69.8 2668.21   259.3 2663.35   408.9 2658.58   568.5 2652.54
   817.8 2646.11   927.3 2642.75   937.4 2642.33   947.3 2642.55   957.3 2645.34
   977.2 2655.13   987.2 2659.32  1007.1 2666.07    1037 2674.66  1086.8 2686.74
  1096.8 2689.88  1106.8 2693.93  1176.6 2727.39  1186.5 2731.92  1196.5 2735.74
  1206.4 2738.82  1246.3 2749.28  1286.2  2759.2    1326 2767.11  1385.8 2776.71
  1435.7 2783.44  1515.4 2792.76  1694.8 2824.04  1724.7 2826.03  1744.6 2825.52
#Mann= 3 , 0 , 0
       0      .1       0   927.3    .045       0   947.3      .1       0
Bank Sta=927.3,947.3
XS Rating Curve= 0 ,0
Exp/Cntr=0.3,0.1

Type RM Length L Ch R = 1 ,5504.1  ,503.8,494.7,485.6
XS GIS Cut Line= 3
     2064130.211      401375.845     2063378.167       401004.47
     2062737.763      401294.001
#Sta/Elev= 30
       0 2664.98   169.8  2656.8   329.5 2647.43   399.4 2644.44   489.3  2644.7
   579.1 2646.59     679 2644.42   758.9 2639.06   917.8 2631.15   927.8 2630.51
   937.8 2631.48   947.6 2636.08   967.4 2647.79   997.1 2662.93  1016.9 2672.65
  1026.8 2676.24  1036.7 2676.71  1066.4 2670.14  1076.3 2670.02  1115.9  2679.2
  1135.7 2685.83  1195.1 2708.52  1254.5 2734.21  1274.3    2742  1333.7 2759.39
  1353.5 2761.88  1422.8 2765.03  1462.4 2764.81  1511.9 2762.58  1541.6 2764.97
#Mann= 3 , 0 , 0
       0      .1       0   917.8    .045       0   937.8      .1       0
Bank Sta=917.8,937.8
XS Rating Curve= 0 ,0
Exp/Cntr=0.3,0.1

Type RM Length L Ch R = 1 ,5009.4  ,694.1,701.3,708.4
XS GIS Cut Line= 2
     2063619.555      400179.416     2062671.922      401011.828
#Sta/Elev= 30
       0 2731.66    80.1 2707.08   140.2 2689.24   200.2 2674.19   240.2 2665.66
   280.3 2658.31   430.4 2635.05   570.6 2616.85   580.6 2616.49   590.6 2617.04
   660.7 2627.49   700.7 2634.03   740.8 2641.75   820.9 2657.96   840.9 2661.69
   890.9 2670.07   900.9 2670.76     911 2670.78     951 2669.75     961 2669.04
     971 2667.72    1001 2661.69    1011 2660.64  1021.1 2661.13  1071.1 2671.71
  1091.1  2675.4  1101.2 2676.77  1111.2 2677.63  1171.2 2680.57  1261.3 2682.34
#Mann= 3 , 0 , 0
       0      .1       0   570.6    .045       0   590.6      .1       0
Bank Sta=570.6,590.6
XS Rating Curve= 0 ,0
Exp/Cntr=0.3,0.1

Type RM Length L Ch R = 1 ,4308.1  ,381.8,377.8,373.9
XS GIS Cut Line= 3
     2063114.386      399468.039     2062834.303      400003.123
     2062052.578      400416.978
#Sta/Elev= 30
       0 2717.64    39.6 2712.21   108.9 2699.24   128.7 2696.02     198 2688.54
     297 2674.52   316.8 2671.31   346.5 2665.39   366.3 2660.67   386.1 2655.11
   415.8 2645.98   445.5 2638.02   465.3 2633.89   514.8 2624.82   524.8 2623.37
     604 2619.96   762.9 2611.41   772.9 2610.93   782.9 2610.99   822.6 2614.88
   931.9 2623.25  1001.5 2629.11  1071.1 2636.45  1110.8 2641.74  1150.6 2643.66
  1180.4 2645.98  1269.8 2658.53  1389.1 2674.17  1428.8 2681.59  1488.5 2694.42
#Mann= 3 , 0 , 0
       0      .1       0   762.9    .045       0   782.9      .1       0
Bank Sta=762.9,782.9
XS Rating Curve= 0 ,0
Exp/Cntr=0.3,0.1

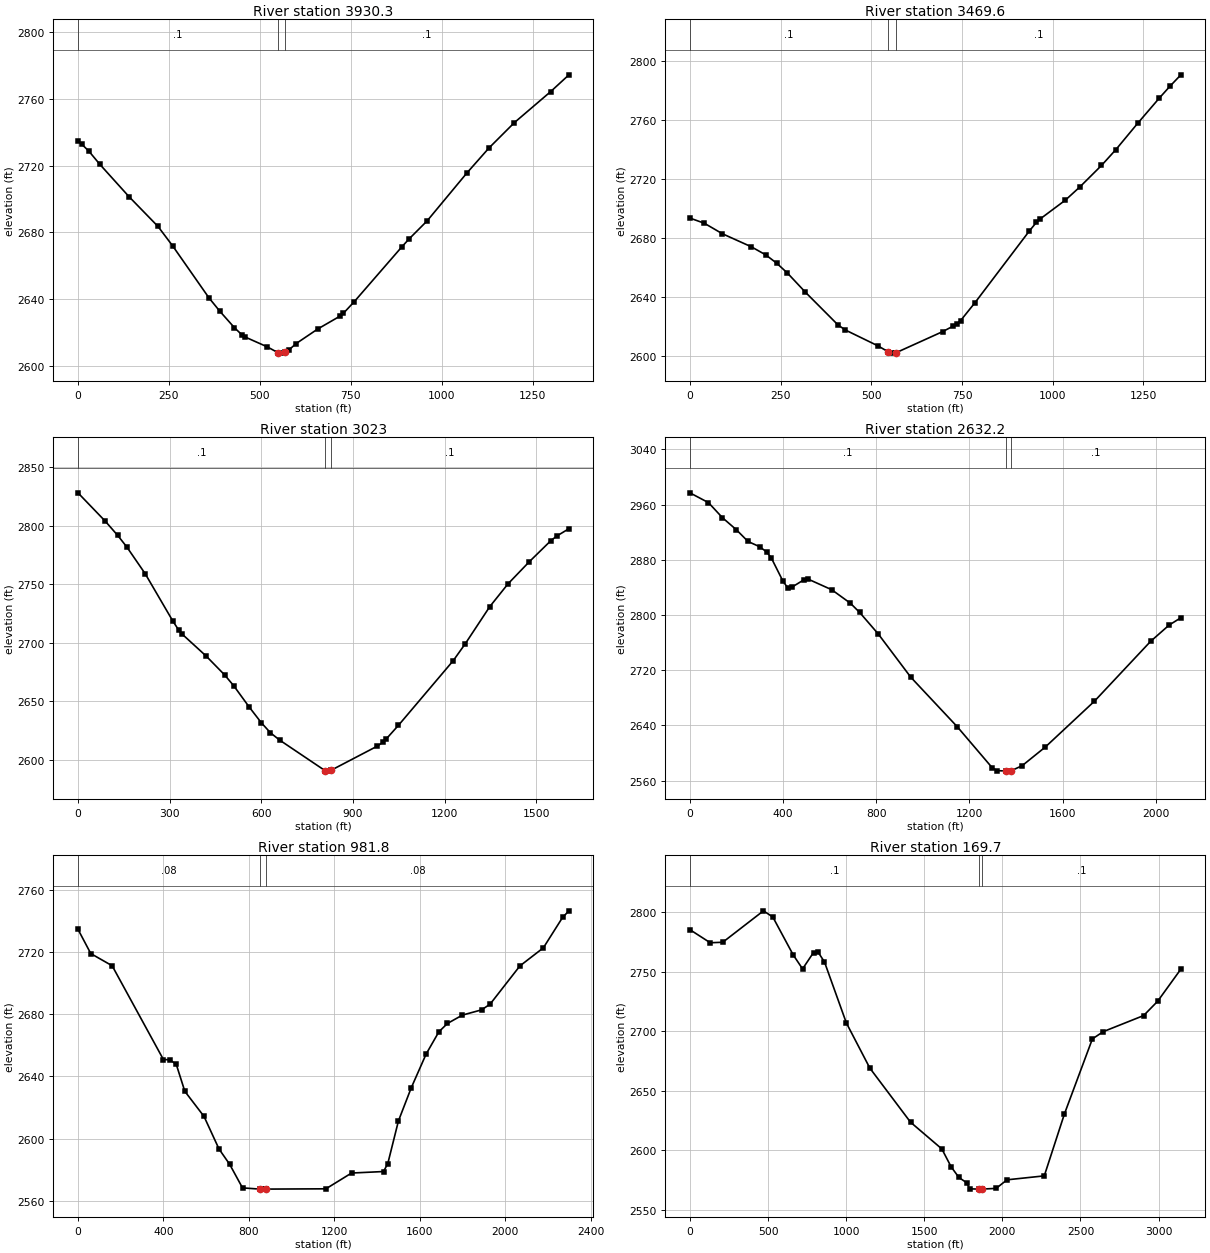
Type RM Length L Ch R = 1 ,3930.3  ,471.1,460.7,450.2
XS GIS Cut Line= 2
     2062935.676      399441.389       2061835.2      400222.069
#Sta/Elev= 30
       0 2734.68      10 2732.99      30 2728.72      60 2720.85   139.9 2701.55
   219.9 2683.63   259.9 2672.07   359.8 2640.89   389.8 2632.83   429.8    2623
   449.8 2618.84   459.8 2617.33   519.7 2611.52   549.7 2607.99   559.7 2607.71
   569.7 2608.18   579.7 2609.63   599.7 2613.45   659.6 2622.26   719.6  2629.8
   729.6 2631.61   759.6 2638.61   889.5 2671.24   909.5 2676.02   959.5 2686.93
  1069.4 2715.79  1129.4 2730.59  1199.3 2745.81  1299.3 2764.44  1349.3 2774.46
#Mann= 3 , 0 , 0
       0      .1       0   549.7    .045       0   569.7      .1       0
Bank Sta=549.7,569.7
XS Rating Curve= 0 ,0
Exp/Cntr=0.3,0.1

Type RM Length L Ch R = 1 ,3469.6  ,459.1,446.5,433.9
XS GIS Cut Line= 2
     2062550.039      398932.954     2061772.494      400040.746
#Sta/Elev= 30
       0 2693.43    39.8 2689.93    89.6  2682.8   169.2 2673.99     209  2668.5
   238.8 2662.95   268.7 2656.21   318.4 2643.19     408 2621.08   427.9 2617.66
   517.5 2606.95   547.3 2602.73   557.3 2601.91   567.3 2602.09   696.6 2616.47
   726.5 2620.32   736.4 2621.84   746.4 2624.02   786.2  2636.2   935.5 2684.63
   955.4 2690.58   965.3  2692.8    1035 2705.58  1074.8  2714.5  1134.5 2729.07
  1174.3 2739.85    1234 2757.55  1293.7 2774.67  1323.6 2782.85  1353.4 2790.51
#Mann= 3 , 0 , 0
       0      .1       0   547.3    .045       0   567.3      .1       0
Bank Sta=547.3,567.3
XS Rating Curve= 0 ,0
Exp/Cntr=0.3,0.1

Type RM Length L Ch R = 1 ,3023    ,409.5,390.8,372.1
XS GIS Cut Line= 3
     2061659.625      398416.159     2061832.064       399156.08
     2061669.031      399986.924
#Sta/Elev= 30
       0 2827.93      90 2803.54     130 2791.59     160 2781.67   219.9 2758.93
   309.9 2718.74   329.9 2710.67   339.9  2707.6   419.9 2688.53   479.8 2672.57
   509.8 2663.27   559.8 2645.32   599.8  2631.8   629.8 2623.17   659.8 2616.96
   809.5 2590.71   819.5 2590.46   829.5 2591.37   978.9 2611.72   998.8 2615.34
  1008.8 2617.95  1048.6 2629.54  1227.9 2684.73  1267.8 2699.36  1347.4 2730.82
  1407.2 2750.29  1476.9 2769.18  1546.7 2786.97  1566.6 2791.06  1606.4 2797.31
#Mann= 3 , 0 , 0
       0      .1       0   809.5    .045       0   829.5      .1       0
Bank Sta=809.5,829.5
XS Rating Curve= 0 ,0
Exp/Cntr=0.3,0.1

Type RM Length L Ch R = 1 ,2632.2  ,1633.4,1650.4,1667.2
XS GIS Cut Line= 4
     2061060.137       397938.88     2061414.625      399145.543
     2061492.416      399317.219     2061631.902      399963.685
#Sta/Elev= 30
       0 2977.07    79.8 2962.83   139.7 2941.02   199.6 2923.52   249.5 2906.57
   299.4 2898.96   329.4 2891.36   349.4 2882.74   399.3 2849.15   419.2 2839.71
   439.2 2840.63   489.1    2851     509 2851.77   608.9 2836.61   688.7 2817.13
   728.6 2803.76   808.5 2772.53   948.2 2709.83  1147.9 2637.95  1297.3 2578.77
  1317.2 2574.53  1356.8 2573.82  1366.8 2573.73  1376.8 2573.96  1426.3 2581.62
  1526.3 2608.84  1736.7 2675.14  1977.2 2761.66  2057.4 2785.49  2107.5 2795.98
#Mann= 3 , 0 , 0
       0      .1       0  1356.8    .045       0  1376.8      .1       0
Bank Sta=1356.8,1376.8
XS Rating Curve= 0 ,0
Exp/Cntr=0.3,0.1

Type RM Length L Ch R = 1 ,981.8   ,861.3,812.1,762.8
XS GIS Cut Line= 4
     2060222.879      398253.967      2059949.17      398920.164
     2059879.452      399415.938     2060827.736      399927.877
#Sta/Elev= 30
       0 2734.88      60 2719.23     160 2711.38   400.1 2650.91   430.1 2650.76
   460.2 2647.82   500.2 2630.45   590.2 2614.23   660.2 2593.28   710.2 2583.37
   770.3 2568.19   850.4  2567.4  865.52 2567.38   880.4  2567.4  1160.8 2567.58
  1280.8 2577.75  1430.4 2578.72  1450.4  2583.8  1500.3 2611.34  1560.1 2632.64
    1630 2654.47  1689.9 2668.84  1729.8 2674.17  1799.6 2679.56  1889.4 2682.93
  1929.3 2686.59    2069 2711.26  2178.8 2722.93  2268.6 2742.49  2298.5 2746.78
#Mann= 3 , 0 , 0
       0     .08       0   850.4    .045       0   880.4     .08       0
Bank Sta=850.4,880.4
XS Rating Curve= 0 ,0
Exp/Cntr=0.3,0.1

Type RM Length L Ch R = 1 ,169.7   ,175.1,169.7,164.5
XS GIS Cut Line= 4
     2058733.382      398121.967     2059301.909      399631.072
     2060054.371      399693.777     2060781.752       399961.32
#Sta/Elev= 30
       0 2785.52   130.2 2774.52   210.3 2774.93   470.8 2801.36   530.9 2796.13
   661.1 2764.33   721.2 2752.55   791.3 2766.32   821.4 2766.47   861.4 2758.38
  1001.6 2707.05  1151.9  2669.1  1412.3 2623.63  1612.6 2601.17  1672.3 2586.08
  1721.9 2577.17  1771.6 2572.72  1791.4 2567.59  1851.1  2567.4 1860.73 2567.36
    1871  2567.4  1960.4 2567.99  2029.9 2575.19  2268.4 2578.51  2397.5 2630.63
  2576.4 2693.69  2645.9 2699.77  2904.3  2713.3  2993.7 2725.26  3142.7 2752.34
#Mann= 3 , 0 , 0
       0      .1       0  1851.1    .045       0    1871      .1       0
Bank Sta=1851.1,1871
XS Rating Curve= 0 ,0
Exp/Cntr=0.3,0.1

Chan Stop Cuts=-1
Use User Specified Reach Order=0
Composite Channel Slope=5